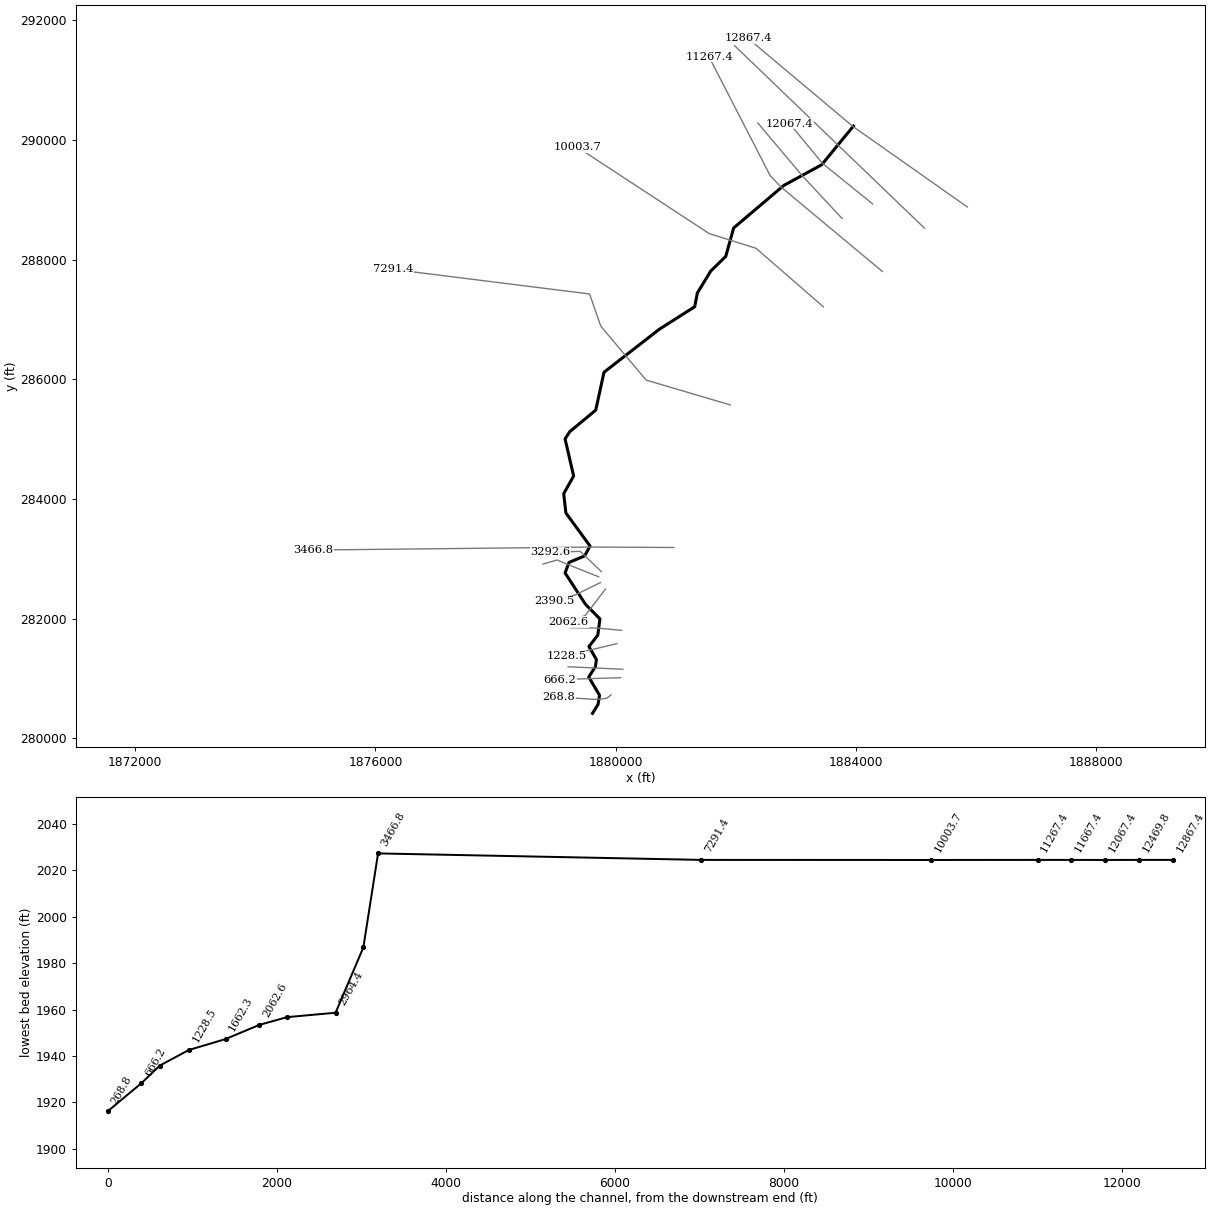
--- StphnsLk.prj (project) ---

Proj Title=StphnsLk
Current Plan=p01
Default Exp/Contr=0,0
English Units
Geom File=g01
Flow File=f01
Plan File=p01
BEGIN DESCRIPTION:
END DESCRIPTION:
DSS Export Rating Curves= 0
DSS Export Rating Curve Sorted= 0
DSS Export Volume Flow Curves= 0
DXF OffsetX= 0
DXF OffsetY= 0
DXF ScaleX= 0
DXF ScaleY= 0

--- StphnsLk.p01 (plan) ---

Plan Title=Floodplain
Program Version=4.00
Geom File=g01
Flow File=f01
K Sum by GR=0
Std Step Tol=0.01
Critical Tol=0.01
Num of Std Step Trials=20
Max Error Tol=0.3
Flow Tol Ratio=0.001
Split Flow NTrial=30
Split Flow Tol=0.02
Split Flow Ratio=0.02
Log Output Level=0
Friction Slope Method=1
Unsteady Friction Slope Method=2
Unsteady Bridges Friction Slope Method=1
Global Log Level=0
CheckData=False
Run HTab=0
Run UNet=0
Run PostProcess=0
UNET Theta=0
UNET Theta Warmup=0
UNET ZTol=0
UNET ZSATol=0
UNET MxIter=0
UNET MaxInSteps=0
UNET DtIC=0
UNET DtMin=0
UNET MaxCRTS=0
UNET WFStab=0
UNET SFStab=0
UNET WFX=0
UNET SFX=0
UNET DSS MLevel=0
UNET DZMax Abort=0
UNET Convert EG Bridges=0
UNET Use Existing IB Tables=0
UNET Froude Limit=0
UNET Froude Power=0
Write IC File=0
Echo Input=False
Echo Output=False
Write Detailed=0

--- StphnsLk.f01 (steady flow) ---

Flow Title=NFF Regression Equation
Program Version=4.00
Number of Profiles=1
Profile Names=P100yr
River Rch & RM=StphnsLk,Main      ,12867.4
732.0499
River Rch & RM=StphnsLk,Main      ,12067.4
982.1868
River Rch & RM=StphnsLk,Main      ,11267.4
1007.708
River Rch & RM=StphnsLk,Main      ,10003.7
1130.957
River Rch & RM=StphnsLk,Main      ,7291.4
1230.163
River Rch & RM=StphnsLk,Main      ,3466.8
1362.415
River Rch & RM=StphnsLk,Main      ,268.8
1511.967
Boundary for River Rch & Prof#=StphnsLk,Main      ,1
Up Type=0
Dn Type=3
Dn Slope=0.028195

--- StphnsLk.g01 (geometry) ---

Geom Title=USGS 3m DEM
Program Version=4.10

River Reach=StphnsLk        ,Main
Reach XY= 30
     1883960.415      290232.518     1883432.678      289586.545
     1882800.674      289240.402     1881965.939       288530.02
     1881834.037      288053.822     1881585.604      287811.242
     1881361.264      287443.106      1881317.21      287213.823
     1880725.782      286835.237     1879806.934      286118.376
     1879669.686      285485.752      1879237.13      285125.268
     1879158.429       285004.76     1879301.654      284384.823
     1879135.896      284089.264      1879172.45      283766.959
      1879574.97        283213.6     1879483.788      283048.181
     1879224.582      282940.079     1879159.221      282764.064
     1879500.039      282239.424     1879739.052      281997.033
     1879703.876      281724.805     1879556.287      281533.463
     1879680.623      281317.531     1879664.784      281198.585
     1879552.761      281025.352     1879732.501      280720.554
     1879707.748      280566.856     1879615.494      280417.469

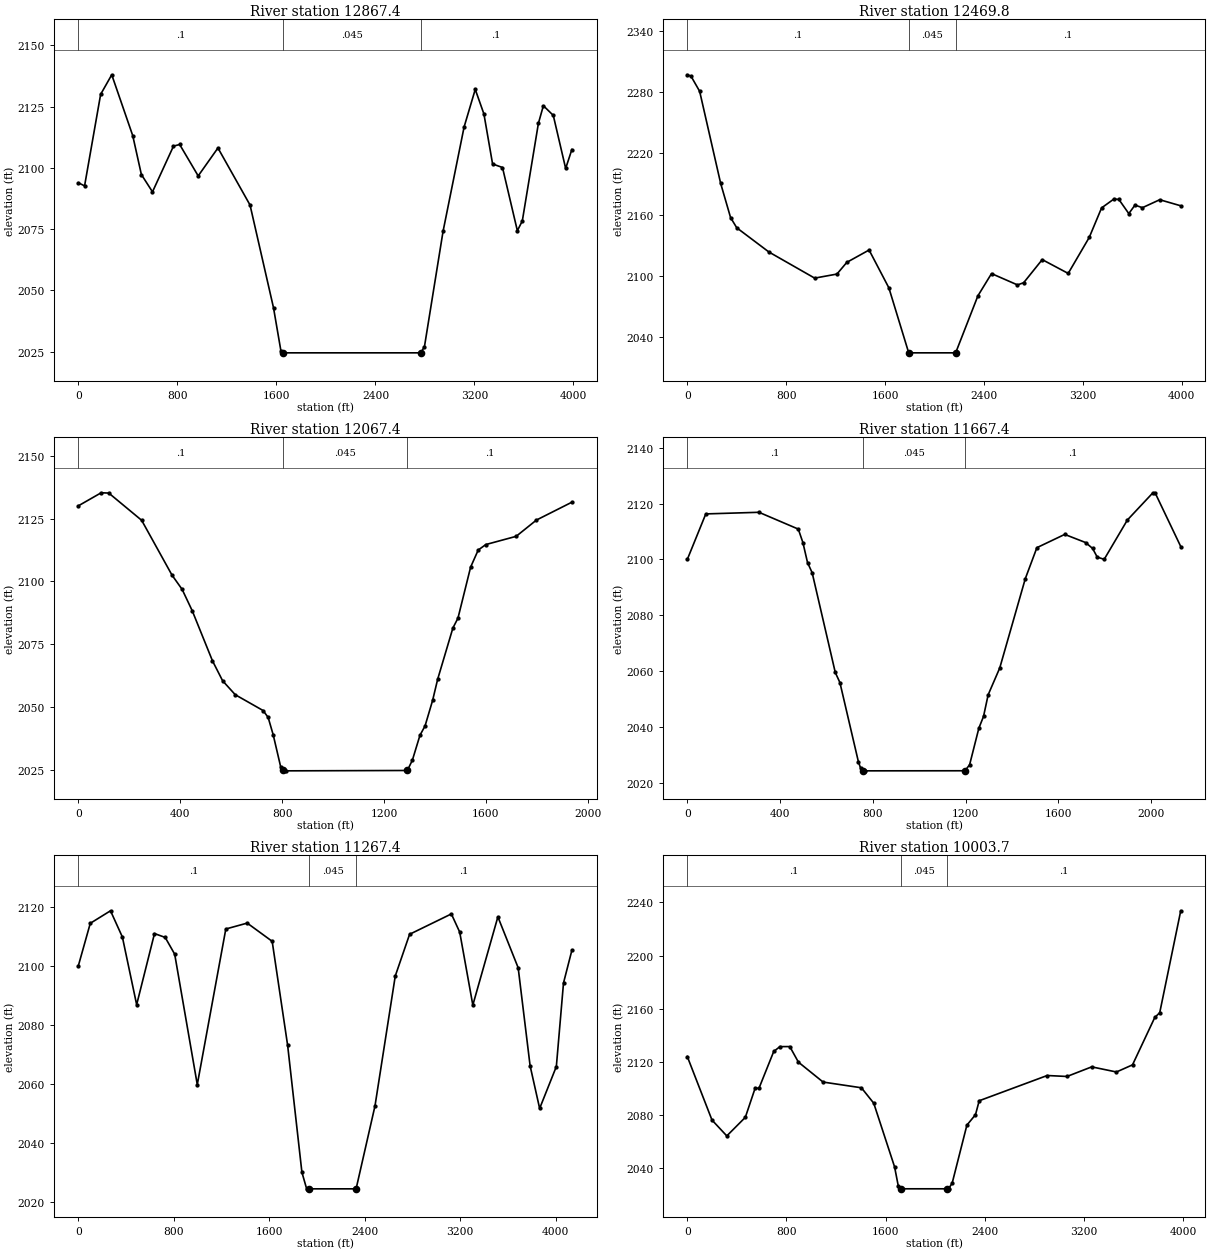
Type RM Length L Ch R = 1 ,12867.4 ,401.1,397.6,396.1
XS GIS Cut Line= 3
     1885857.648      288880.791     1883954.053      290224.803
     1882204.939      291699.177
#Sta/Elev= 30
       0 2093.89    49.9 2092.63   179.6 2129.97   269.4 2137.97     439 2113.14
   508.8 2097.26   598.6 2090.19   768.2 2108.85   818.1 2109.52   967.8  2096.7
  1127.4  2108.1  1386.8 2084.81  1576.4 2042.88  1636.2 2025.29  1656.2  2024.5
    2766  2024.5    2796 2027.04  2946.2 2074.06  3116.3 2116.67  3206.4 2132.01
  3276.4 2121.98  3346.4 2101.58  3426.5 2100.13  3546.6 2074.33  3586.6 2078.33
  3716.7 2118.17  3756.8 2125.34  3836.8  2121.4  3936.9 2099.74  3986.9 2107.46
#Mann= 3 , 0 , 0
       0      .1       0  1656.2    .045       0    2766      .1       0
Bank Sta=1656.2,2766
XS Rating Curve= 0 ,0
Exp/Cntr=0.3,0.1

Type RM Length L Ch R = 1 ,12469.8 ,400.4,402.4,399.6
XS GIS Cut Line= 2
     1885145.421      288524.678     1881981.096      291577.081
#Sta/Elev= 30
       0 2296.87      30 2295.51     100 2280.68   270.1 2190.38   350.1 2157.01
   400.1 2146.98   660.2 2123.27  1030.3 2097.69  1210.4 2101.66  1290.4 2113.14
  1470.4 2125.22  1630.5 2088.16  1790.5 2024.69  1800.5  2024.5  2170.6  2024.5
  2350.7 2080.37  2460.7 2102.13  2670.8 2091.03  2720.8  2093.2  2870.9 2115.82
  3080.9  2102.3    3251 2137.54    3351 2166.48    3451 2175.21    3491 2174.72
  3571.1 2160.89  3621.1 2169.22  3681.1 2166.68  3821.2 2174.48  3991.2 2168.54
#Mann= 3 , 0 , 0
       0      .1       0  1790.5    .045       0  2170.6      .1       0
Bank Sta=1790.5,2170.6
XS Rating Curve= 0 ,0
Exp/Cntr=0.3,0.1

Type RM Length L Ch R = 1 ,12067.4 ,403.4,400,400.1
XS GIS Cut Line= 3
     1884280.573      288931.665     1883447.229      289607.706
     1882896.817      290274.722
#Sta/Elev= 30
       0 2130.11    89.4  2135.3   119.2 2135.19   248.4 2124.33   367.6 2102.48
   407.4 2096.79   447.1 2088.26   526.6  2068.3   566.4 2060.36     616 2054.81
   725.3 2048.51   745.2 2045.76   765.1  2038.8   794.9 2025.84   804.8 2024.67
   814.7 2024.47  1291.8 2024.61  1311.6 2028.72  1341.5 2038.68  1361.3 2042.34
  1391.2  2052.6    1411 2061.02  1470.7  2081.4  1490.6 2085.32  1540.3 2105.66
  1570.1 2112.47  1599.9 2114.66  1719.2 2117.94  1798.7 2124.42  1937.9 2131.54
#Mann= 3 , 0 , 0
       0      .1       0   804.8    .045       0  1291.8      .1       0
Bank Sta=804.8,1291.8
XS Rating Curve= 0 ,0
Exp/Cntr=0.3,0.1

Type RM Length L Ch R = 1 ,11667.4 ,397.1,400,401.5
XS GIS Cut Line= 3
     1883771.839      288687.473     1883107.542      289403.819
     1882367.734      290284.897
#Sta/Elev= 30
       0 2100.01    79.8 2116.28     309 2116.86   478.5 2110.86   498.4 2106.06
   518.4 2098.89   538.3 2095.28     638 2059.64     658 2056.03   737.7 2027.74
   747.7 2025.34   757.6 2024.58   767.6  2024.5    1197 2024.53  1217.1 2026.66
  1257.1 2039.76  1277.1 2043.92  1297.1 2051.66  1347.1 2061.25  1457.2 2093.14
  1507.2 2104.22  1627.2 2108.96  1717.3 2106.05  1747.3 2103.95  1767.3 2100.86
  1797.3 2100.05  1897.3  2114.1  2007.4 2123.83  2017.4 2123.72  2127.4 2104.63
#Mann= 3 , 0 , 0
       0      .1       0   757.6    .045       0    1197      .1       0
Bank Sta=757.6,1197
XS Rating Curve= 0 ,0
Exp/Cntr=0.3,0.1

Type RM Length L Ch R = 1 ,11267.4 ,1254.4,1263.7,1275.4
XS GIS Cut Line= 4
     1884443.368      287802.276      1882764.56      289205.704
     1882575.037      289402.962     1881553.759      291393.937
#Sta/Elev= 30
       0 2100.26    99.6  2114.6   269.1 2118.85   368.7 2109.94   488.3 2086.99
   637.8 2111.12   727.5 2109.81   807.2 2104.12   996.5 2059.87  1235.7 2112.67
  1415.1 2114.67  1624.3 2108.49  1753.9  2073.2  1873.5 2030.13  1913.3  2024.5
  1933.3  2024.5  2327.8  2024.5  2486.2 2052.64  2656.2 2096.73  2776.2 2110.87
  3126.3 2117.78  3196.3 2111.62  3306.3 2086.85  3516.3 2116.79  3686.4 2099.51
  3786.4 2066.25  3866.4 2051.78  4006.4    2066  4066.4 2094.35  4136.4 2105.41
#Mann= 3 , 0 , 0
       0      .1       0  1933.3    .045       0  2327.8      .1       0
Bank Sta=1933.3,2327.8
XS Rating Curve= 0 ,0
Exp/Cntr=0.3,0.1

Type RM Length L Ch R = 1 ,10003.7 ,2726,2712.3,2698.6
XS GIS Cut Line= 4
     1883458.282      287213.392     1882340.065      288189.745
     1881557.388      288437.259     1879366.204       289877.91
#Sta/Elev= 30
       0 2124.04   199.3 2076.23   318.8 2064.29   468.3 2078.28     548 2100.41
   577.8 2100.02   697.4 2127.83   747.2 2131.49   826.9 2131.53   896.7 2119.79
  1095.9 2104.82  1404.8 2100.52  1504.3 2088.92  1672.4 2041.02  1702.1 2026.72
  1721.8  2024.5  2097.7  2024.5  2107.6 2024.47  2137.2 2028.78  2255.9  2072.4
  2325.3 2080.27  2355.2 2090.76  2903.9 2109.75  3063.5 2109.03    3263 2116.26
  3462.6  2112.4  3592.2 2117.78  3771.8 2153.43  3811.7 2157.02  3981.3 2233.72
#Mann= 3 , 0 , 0
       0      .1       0  1721.8    .045       0  2097.7      .1       0
Bank Sta=1721.8,2097.7
XS Rating Curve= 0 ,0
Exp/Cntr=0.3,0.1

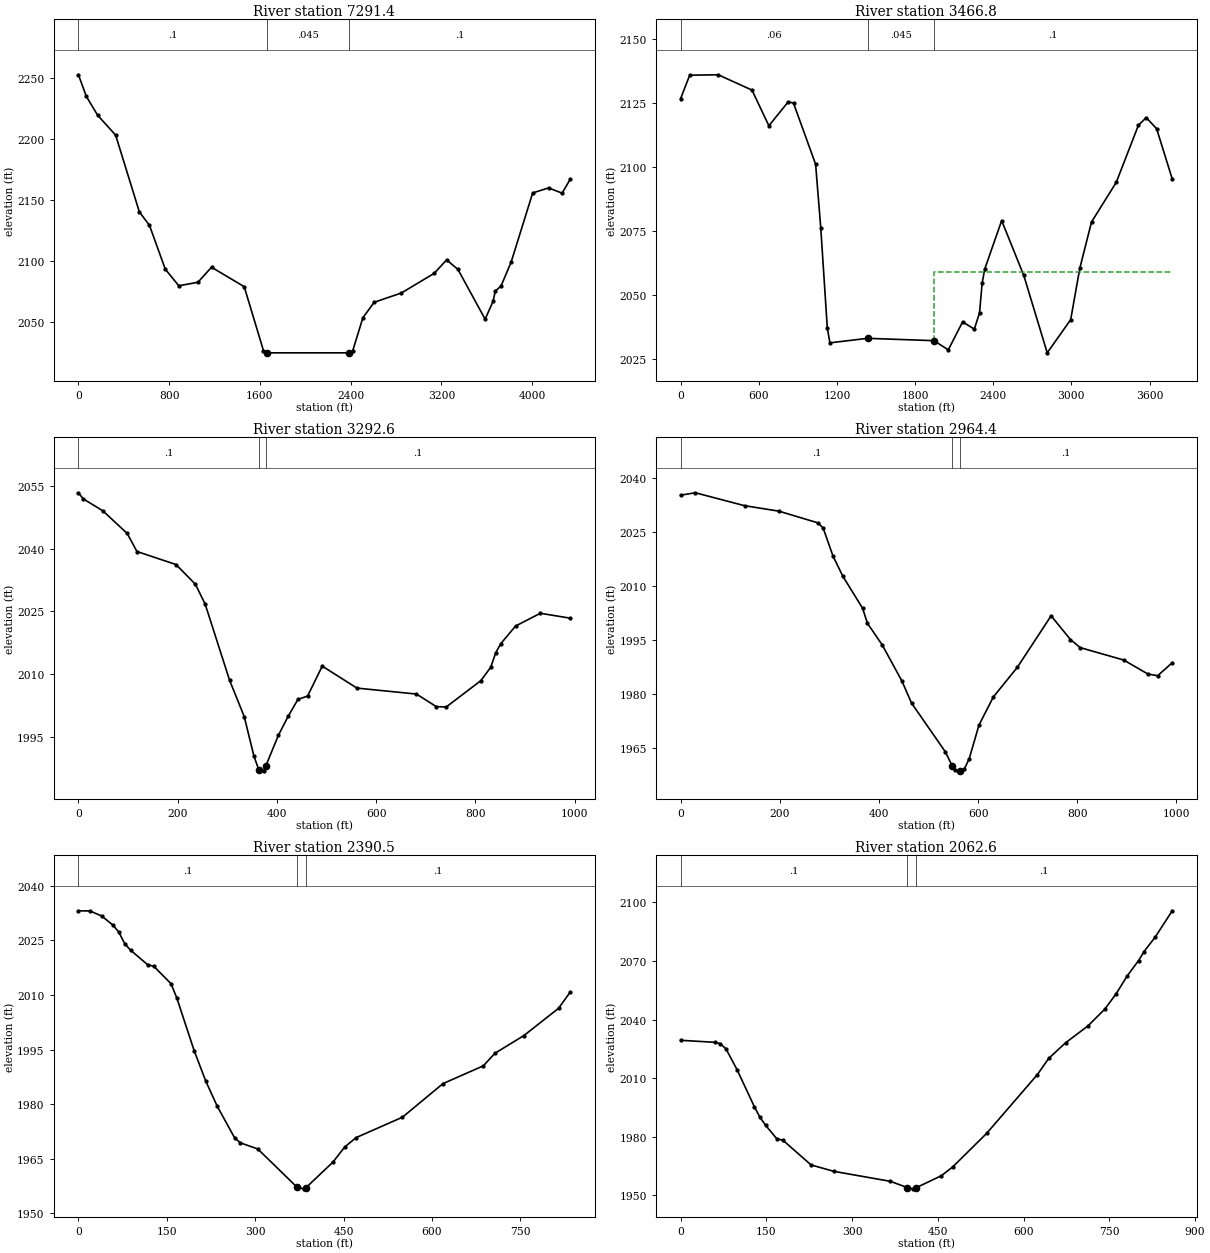
Type RM Length L Ch R = 1 ,7291.4  ,3802.8,3824.6,3846.2
XS GIS Cut Line= 5
      1881909.26      285572.576     1880508.099      285987.996
     1879753.229      286889.969     1879567.329      287426.697
     1876301.297      287836.958
#Sta/Elev= 30
       0 2252.33    69.6 2234.64     169 2219.22   328.1 2202.85   536.9 2140.01
   626.3 2128.93   765.5 2093.07   884.8 2079.44  1053.8 2082.34  1173.1 2094.64
  1461.4 2078.72  1630.9 2026.39  1660.8  2024.5  2388.4  2024.5  2418.3 2026.29
    2508 2053.38  2607.7 2065.95  2846.9 2073.54  3135.9 2089.61  3245.6 2100.66
  3345.4 2092.87  3585.1 2052.08    3655 2066.62  3674.9 2075.13  3724.9 2079.14
  3814.7 2098.91  4004.4 2155.51  4144.2 2159.63    4264 2155.34    4334 2166.57
#Mann= 3 , 0 , 0
       0      .1       0  1660.8    .045       0  2388.4      .1       0
Bank Sta=1660.8,2388.4
XS Rating Curve= 0 ,0
Exp/Cntr=0.3,0.1

Type RM Length L Ch R = 1 ,3466.8  ,192,174.2,156.5
XS GIS Cut Line= 3
     1880971.045      283189.781     1879615.696      283196.901
     1874966.113      283147.125
#Sta/Elev= 30
       0 2126.77    69.8 2135.94     289 2136.11   548.1 2130.11   677.7 2116.16
   827.2 2125.58     867 2124.97  1036.5  2101.1  1076.3 2076.07  1126.2 2037.11
  1146.1 2031.21  1435.3 2032.98  1945.2 2032.06  2055.1 2028.47  2165.1 2039.42
    2255 2036.56    2295 2042.98    2315 2054.54    2335 2060.11    2465 2079.04
  2634.9 2057.57  2814.8  2027.3  2994.8 2040.28  3064.8 2060.38  3154.7  2078.5
  3344.7 2094.02  3514.6 2116.33  3574.6 2119.35  3654.6 2115.02  3774.5 2095.34
#Mann= 3 , 0 , 0
       0     .06       0  1435.3    .045       0  1945.2      .1       0
#XS Ineff= 2 , 0
         1113.06 2045.24 1949.12         2058.94
Permanent Ineff=
       F       F
Bank Sta=1435.3,1945.2
XS Rating Curve= 0 ,0
Exp/Cntr=0.3,0.1

Type RM Length L Ch R = 1 ,3292.6  ,319.9,328.2,336.5
XS GIS Cut Line= 3
     1879764.571      282786.319     1879409.251      283125.611
      1878910.22      283106.304
#Sta/Elev= 30
       0 2053.45     9.8 2051.98    49.1 2049.13    98.3  2043.7   117.9 2039.37
   196.5 2036.25   235.8 2031.51   255.5 2026.71   304.6 2008.49   334.1 1999.79
   353.7 1990.27   363.6    1987   373.4 1986.78   377.5 1987.92   402.9  1995.3
   422.5 1999.83   442.2 2003.89   461.8 2004.72   491.3 2011.89   561.2 2006.62
   681.1 2005.19     721 2002.19     741 2002.08   810.9  2008.4   830.9 2011.63
   840.9 2015.09   850.9 2017.24   880.8 2021.49   930.8 2024.56   990.7 2023.39
#Mann= 3 , 0 , 0
       0      .1       0   363.6    .045       0   377.5      .1       0
Bank Sta=363.6,377.5
XS Rating Curve= 0 ,0
Exp/Cntr=0.3,0.1

Type RM Length L Ch R = 1 ,2964.4  ,554.3,573.7,593.1
XS GIS Cut Line= 4
       1879718.4      282700.365     1879303.801      282865.699
     1879026.022       282981.44     1878791.403      282913.226
#Sta/Elev= 30
       0 2035.11    29.8 2035.77     129 2032.19   198.4 2030.67   277.7 2027.39
   287.6 2025.95   307.5 2018.18   327.3  2012.6     367 2003.74   376.9 1999.55
   406.7 1993.55   446.4 1983.54   465.8 1977.42   533.7 1963.96   548.3  1959.9
   553.1 1958.73   562.8 1958.63   563.3 1958.66   572.5  1959.2   582.2 1962.05
   601.7 1971.28   630.8 1979.13   679.3 1987.37   747.3 2001.64   786.4 1995.04
   805.9 1992.82   893.9 1989.36   942.7 1985.47   962.3 1985.02   991.6 1988.63
#Mann= 3 , 0 , 0
       0      .1       0   548.3    .045       0   563.3      .1       0
Bank Sta=548.3,563.3
XS Rating Curve= 0 ,0
Exp/Cntr=0.3,0.1

Type RM Length L Ch R = 1 ,2390.5  ,317.4,327.9,338.4
XS GIS Cut Line= 3
     1879747.433      282603.708     1879333.505      282399.342
     1878977.645      282287.584
#Sta/Elev= 30
       0 2033.16    19.6  2033.1    39.3 2031.75    58.9 2029.17    68.8 2027.23
    78.6  2024.1    88.4 2022.34   117.9 2018.28   127.7 2017.94   157.2 2013.11
     167  2009.2   196.4 1994.74   216.1 1986.38   235.7 1979.41   265.2 1970.74
     275 1969.38   304.5 1967.69     371  1957.2     383 1956.74     386 1957.02
   432.2 1964.11   451.8  1968.2   471.4 1970.82     550 1976.42   618.7 1985.64
   687.4 1990.55     707 1993.99   756.1 1998.85     815 2006.35   834.6 2010.75
#Mann= 3 , 0 , 0
       0      .1       0     371    .045       0     386      .1       0
Bank Sta=371,386
XS Rating Curve= 0 ,0
Exp/Cntr=0.3,0.1

Type RM Length L Ch R = 1 ,2062.6  ,423.5,400.2,378.7
XS GIS Cut Line= 3
     1879831.442      282495.606     1879495.394      282053.288
     1879210.786      281945.168
#Sta/Elev= 30
       0 2029.39    59.5 2028.36    69.4 2027.67    79.4    2025    99.2  2014.1
     129  1995.4   138.9 1989.96   148.8 1985.88   168.6 1978.89   178.6 1978.36
   228.2 1965.64   267.8 1962.36     367 1957.24   396.6 1954.04   406.7  1953.4
   411.6 1953.91   456.3 1960.14   476.1 1964.63   535.7 1981.89   624.2 2011.88
   643.9 2020.12   673.4 2028.11   712.6 2036.75   742.1 2045.34   761.7 2053.12
   781.4  2062.4     801 2070.11   810.8  2074.8   830.5 2082.31     860 2095.64
#Mann= 3 , 0 , 0
       0      .1       0   396.6    .045       0   411.6      .1       0
Bank Sta=396.6,411.6
XS Rating Curve= 0 ,0
Exp/Cntr=0.3,0.1

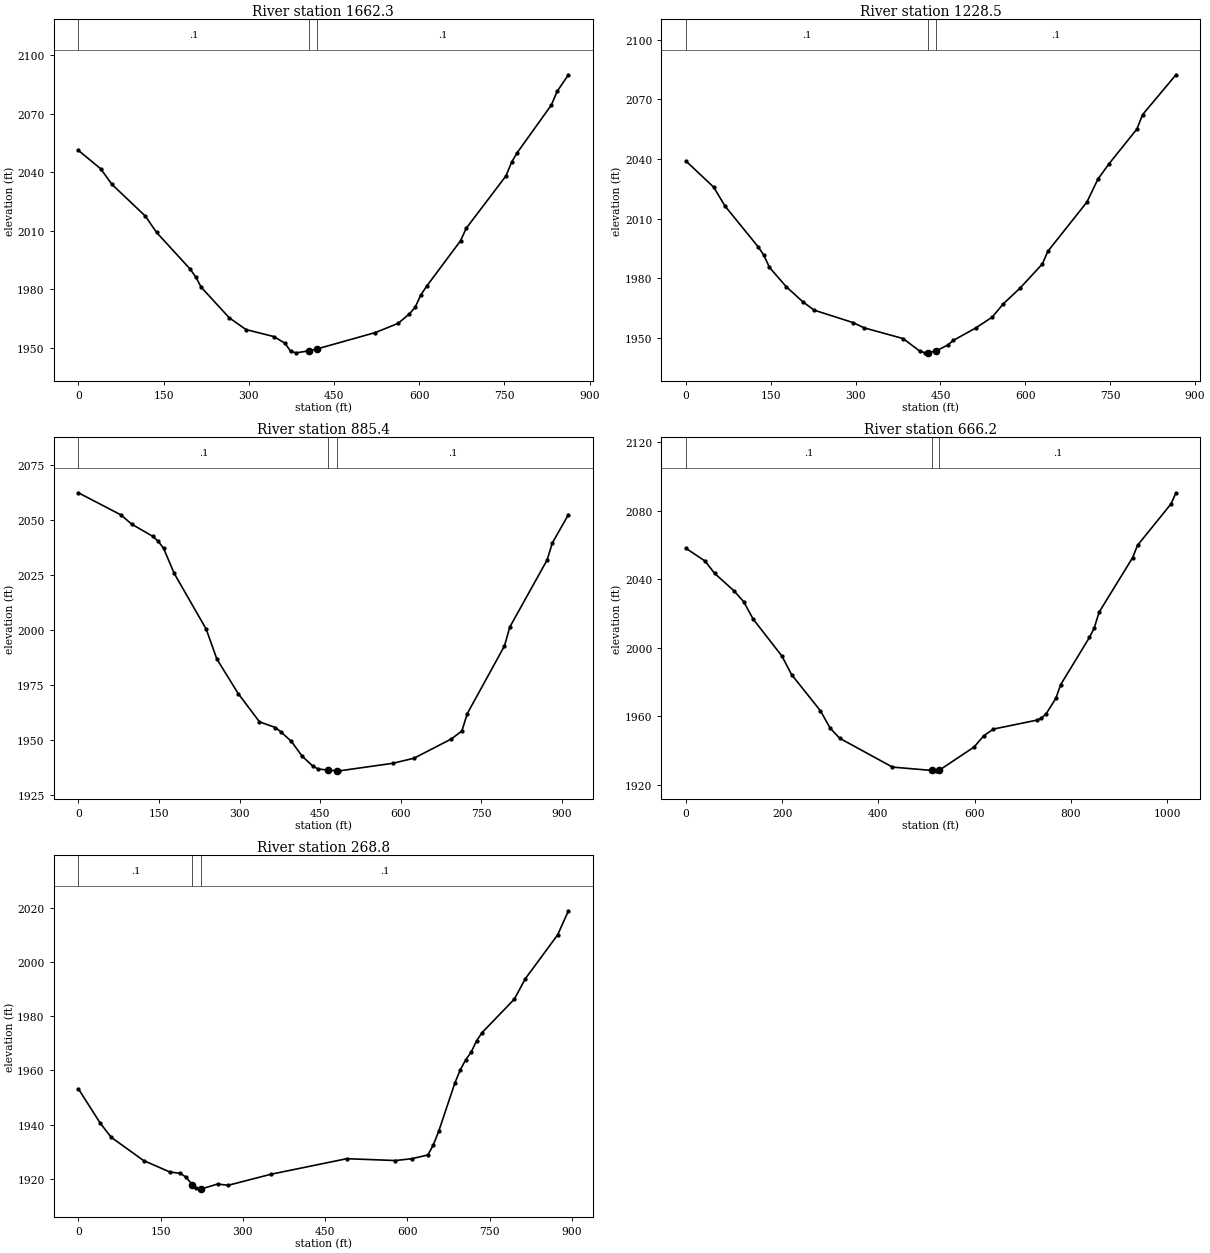
Type RM Length L Ch R = 1 ,1662.3  ,425.1,433.8,437.4
XS GIS Cut Line= 3
     1880101.772      281805.456     1879690.488      281842.693
     1879240.934       281848.76
#Sta/Elev= 30
       0 2051.11    39.3 2041.66      59  2033.7     118 2017.37   137.7 2009.01
   196.6 1990.29   206.5 1986.22   216.3  1980.9   265.5 1965.27     295 1959.22
   344.1 1955.62   363.8 1952.16   373.6 1948.08   383.5 1947.28   405.5 1948.29
   420.5 1949.32   522.9 1957.69   562.8 1962.39   582.8 1967.28   592.8 1970.67
   602.8 1976.95   612.8 1981.36   672.7 2004.76   682.7 2011.17   752.7 2038.02
   762.6 2045.09   772.6 2049.99   832.6 2074.38   842.6 2081.32   862.6 2089.87
#Mann= 3 , 0 , 0
       0      .1       0   405.5    .045       0   420.5      .1       0
Bank Sta=405.5,420.5
XS Rating Curve= 0 ,0
Exp/Cntr=0.3,0.1

Type RM Length L Ch R = 1 ,1228.5  ,347.4,343.3,342.2
XS GIS Cut Line= 3
     1880021.159      281582.475     1879551.832      281471.084
     1879181.525      281370.255
#Sta/Elev= 30
       0 2039.05    49.2 2025.88    68.9 2016.49     128  1995.8   137.8 1991.65
   147.7 1985.55   177.2 1975.88   206.7 1968.26   226.4 1964.07   295.3  1957.8
     315 1955.14   383.9 1949.75   413.5 1943.41   423.3 1942.57   427.4 1942.62
   442.4 1943.54   462.7 1946.46   472.5  1948.8   511.9    1955   541.4 1960.53
   561.1 1967.24   590.6 1975.11     630 1987.24   639.8 1993.66   708.7 2018.35
   728.4 2030.02   748.1 2037.72   797.3 2055.18   807.1 2062.33   866.2 2082.41
#Mann= 3 , 0 , 0
       0      .1       0   427.4    .045       0   442.4      .1       0
Bank Sta=427.4,442.4
XS Rating Curve= 0 ,0
Exp/Cntr=0.3,0.1

Type RM Length L Ch R = 1 ,885.4   ,219.1,218.6,218.1
XS GIS Cut Line= 2
     1880120.983      281154.841     1879210.053      281196.427
#Sta/Elev= 30
       0 2062.35    79.3 2052.28    99.1  2048.1   138.8 2042.49   148.7 2040.27
   158.6 2037.07   178.4 2025.66   237.9 2000.31   257.7 1986.72   297.4 1971.03
     337 1958.16   366.7 1955.57   376.6 1953.66   396.5 1949.23   416.3 1942.54
   436.1 1938.07     446 1936.73   465.4 1936.18   480.4 1935.91   485.7 1935.87
   584.8 1939.29   624.4 1941.59   693.8 1950.34   713.6    1954   723.6 1961.86
   792.9 1992.71   802.8 2001.29   872.2 2031.76   882.1 2039.62   911.9  2052.4
#Mann= 3 , 0 , 0
       0      .1       0   465.4    .045       0   480.4      .1       0
Bank Sta=465.4,480.4
XS Rating Curve= 0 ,0
Exp/Cntr=0.3,0.1

Type RM Length L Ch R = 1 ,666.2   ,396.9,397.4,397.4
XS GIS Cut Line= 2
     1880085.338      281014.241     1879067.472      280982.557
#Sta/Elev= 30
       0  2058.2    39.9  2050.7    59.9 2043.48    99.8 2033.38   119.8 2027.11
   139.8 2016.84   199.7 1995.19   219.6 1984.43   279.6 1963.31   299.5  1953.3
   319.5 1947.26   429.3 1930.43   511.5 1928.45   519.2 1928.24   526.5 1928.58
     599 1942.18     619 1948.73     639 1952.62   728.8 1957.81   738.8    1959
   748.8 1961.66   768.8 1970.57   778.7 1978.51   838.6 2006.14   848.6 2011.68
   858.6 2020.83   928.5  2052.8   938.5  2059.9  1008.4 2084.21  1018.4 2090.59
#Mann= 3 , 0 , 0
       0      .1       0   511.5    .045       0   526.5      .1       0
Bank Sta=511.5,526.5
XS Rating Curve= 0 ,0
Exp/Cntr=0.3,0.1

Type RM Length L Ch R = 1 ,268.8   ,286.3,268.8,251.8
XS GIS Cut Line= 5
     1879926.105      280726.993     1879854.815       280672.04
      1879750.85      280654.217     1879624.607      280652.732
     1879054.285      280691.348
#Sta/Elev= 30
       0 1953.23      40 1940.47      60 1935.24   118.8 1926.67   166.7 1922.42
   185.9 1921.92   195.5 1920.61   207.8 1917.76   214.9 1916.42   222.8 1916.22
   224.6 1916.18   253.8 1917.96   273.2  1917.5   351.3 1921.59   489.3 1927.34
     578 1926.66   607.6 1927.33   637.1 1928.72     647  1932.4   656.8 1937.42
   686.4 1955.38   696.3 1960.26   706.1 1963.96     716 1966.77   725.8 1970.93
   735.7 1973.97   794.8 1986.42   814.5 1993.88   873.7 2010.21   893.4 2019.13
#Mann= 3 , 0 , 0
       0      .1       0   207.8    .045       0   222.8      .1       0
Bank Sta=207.8,222.8
XS Rating Curve= 0 ,0
Exp/Cntr=0.3,0.1

Chan Stop Cuts=-1
Use User Specified Reach Order=0
Composite Channel Slope=5